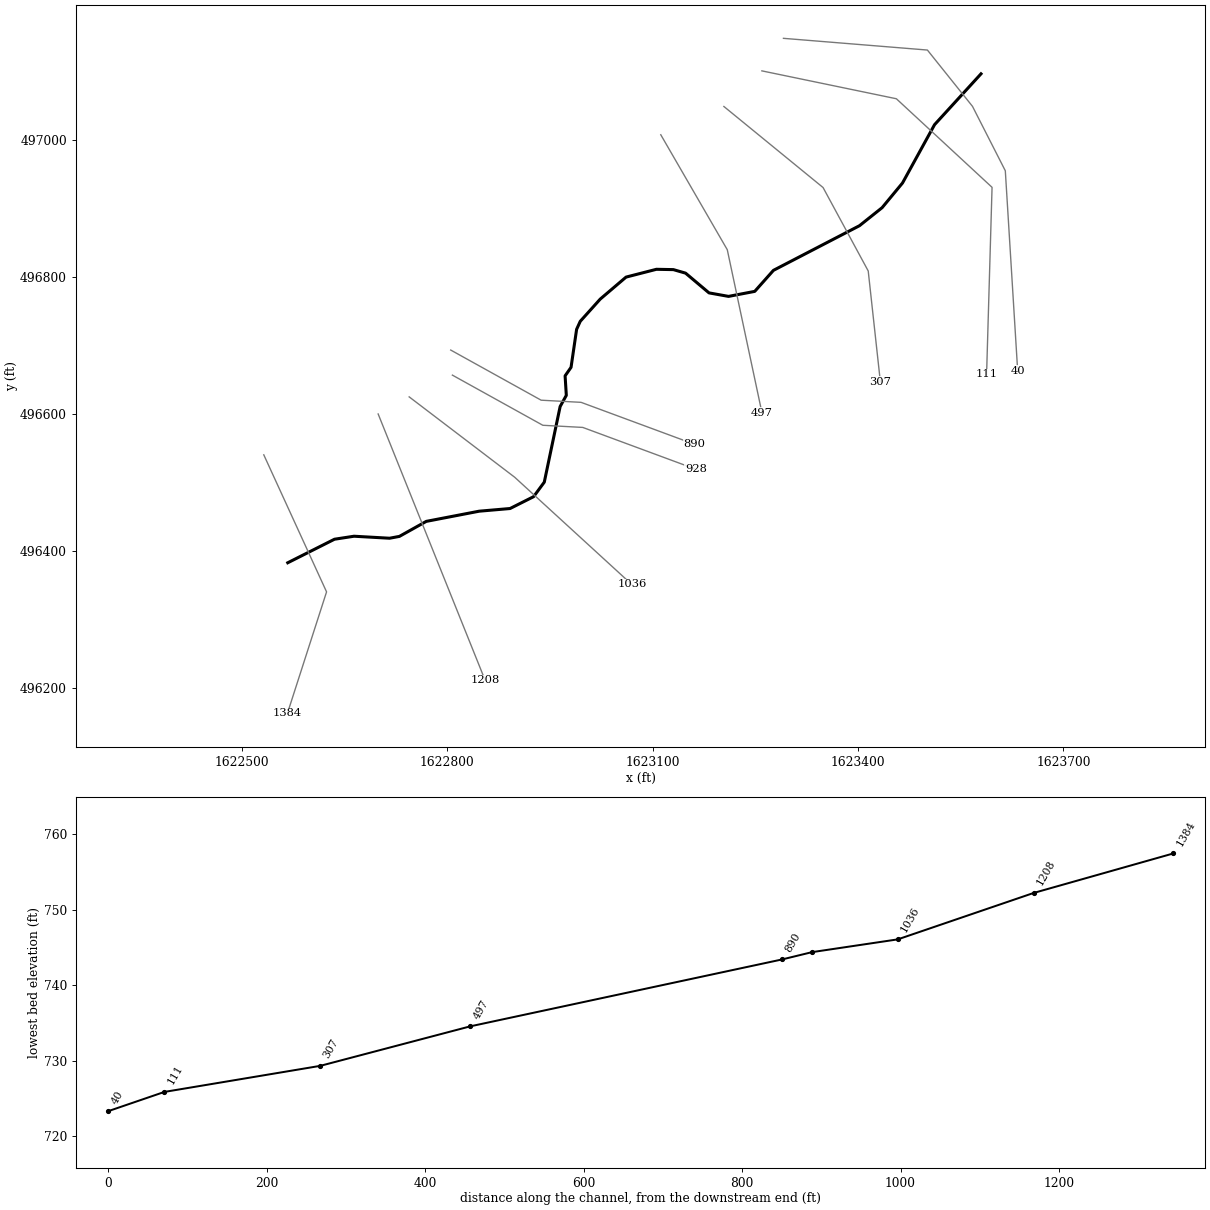
--- GraveCkT2.prj (project) ---

Proj Title=GraveCkT2
Current Plan=p01
Default Exp/Contr=0.3,0.1
English Units
Geom File=g01
Flow File=f01
Plan File=p01
Y Axis Title=Elevation
X Axis Title(PF)=Main Channel Distance
X Axis Title(XS)=Station
BEGIN DESCRIPTION:
---------- MODELED AS PART OF WVEM CTP PROGRAM, 2025----------
Stream Name: Grave Creek Tributary 2
Flood Zone: AFH
Marshall County, WV
HEC-RAS Version: RAS 6.6
Vertical Datum: NAVD88
Projection: NAD 1983 StatePlane West Virginia N FIPS 4701 (US Feet)
Terrain: 1-meter West Virginia FEMA R3 South Central (collected 2018-2019)
Land Use: 2024 NLCD
Hydrologic Method:
Duda et al., "Estimation of magnitude and frequency of floods for rural, unregulated streams in and near Virginia and West Virginia." September 8, 2025.
Additional Model Notes:
None
END DESCRIPTION:
DSS Export Rating Curves= 0
DSS Export Rating Curve Sorted= 0
DSS Export Volume Flow Curves= 0
DXF OffsetX= 0
DXF OffsetY= 0
DXF ScaleX= 1
DXF ScaleY= 10

--- GraveCkT2.p01 (plan) ---

Plan Title=Floodplain
Program Version=6.60
Short Identifier=Floodplain
Geom File=g01
Flow File=f01
Subcritical Flow
K Sum by GR= 0
Std Step Tol= 0.01
Critical Tol= 0.01
Num of Std Step Trials= 20
Max Error Tol= 0.3
Flow Tol Ratio= 0.001
Split Flow NTrial= 30
Split Flow Tol= 0.02
Split Flow Ratio= 0.02
Log Output Level= 0
Friction Slope Method= 1
Unsteady Friction Slope Method= 2
Unsteady Bridges Friction Slope Method= 1
Parabolic Critical Depth
Global Vel Dist= 0 , 0 , 0
Global Log Level= 0
CheckData=True
Encroach Param=-1 ,0,0, 0
Flow Ratio Tolerance=0.1
Flow Ratio Min Ratio=0.5
Flow Ratio Max Ratio=4
Flow Ratio Max Iterations= 10
Computation Interval=1MIN
Output Interval=1HOUR
Instantaneous Interval=1HOUR
Mapping Interval=1HOUR
Computation Time Step Use Courant=        0
Computation Time Step Use Time Series=    0
Computation Time Step Count To Double=0
Computation Time Step Max Doubling=0
Computation Time Step Max Halving=0
Computation Time Step Residence Courant=0
Run HTab= 0
Run UNet= 0
Run Sediment= 0
Run PostProcess= 0
Run WQNet= 0
Run RASMapper=-1
UNET Theta= 1
UNET Theta Warmup= 1
UNET ZTol= 0.02
UNET ZSATol= 0.02
UNET MxIter= 20
UNET Max Iter WO Improvement= 0
UNET MaxInSteps= 0
UNET DtIC= 0
UNET DtMin= 0
UNET MaxCRTS= 20
UNET WFStab= 2
UNET SFStab= 1
UNET WFX= 1
UNET SFX= 1
UNET Gravity=32.17405
UNET 1D Methodology=Finite Difference
UNET DSS MLevel= 4
UNET Pardiso=0
UNET DZMax Abort= 100
UNET Use Existing IB Tables=-1
UNET Froude Reduction=False
UNET Froude Limit= 0.8
UNET Froude Power= 4
UNET D1 Cores= 0
UNET WindReference=Eulerian
UNET WindDragFormulation=Hsu (1988)
UNET D2 Coriolis=0
UNET D2 Cores= 0
UNET D2 Theta= 1
UNET D2 Theta Warmup= 1
UNET D2 Z Tol= 0.01
UNET D2 Volume Tol= 0.01
UNET D2 Max Iterations= 20
UNET D2 Advanced Convergence=0
UNET D2 WS Max Tol=0.15
UNET D2 WS RMS Tol=0.002
UNET D2 WS Stall Tol=1
UNET D2 Equation= 0
UNET D2 RampUpFraction=0.1
UNET D2 TimeSlices= 1
UNET D2 Turbulence Formulation=None
UNET D2 Eddy Viscosity=0.3
UNET D2 Transverse Eddy Viscosity=0.1
UNET D2 Smagorinsky Mixing=0.05
UNET D2 BCVolumeCheck=0
UNET D2 Cores=0
UNET D2 SolverType=PARDISO (Direct)
UNET D2 Minimum Iterations= 3
UNET D2 Maximum Iterations= 30
UNET D2 Restart Number= 10
UNET D2 Relaxation Coeff=1.3
UNET D2 SOR Precondition Iterations= 10
UNET D2 ILUT Maximum Fill= 8
UNET D2 ILUT Tolerance=1E-08
UNET D2 Convergence Tolerance=0.00001
PS Theta= 1
PS WS Tol= 0.01
PS Volume Tol= 0.01
PS Max Iterations= 20
PS Equation= 0
PS Advance Time Step=-1
PS Target Courant=0.9
PS Time Slices= 1
PS Iterate With 2D=0
PS Project Initial WSE from DS=-1
PS Ramp Up Initial WSE from US=-1
PS Cores=0
UNET D1D2 MaxIter= 0
UNET D1D2 ZTol=0.01
UNET D1D2 QTol=0.1
UNET D1D2 MinQTol=1
Write IC File= 0
Write IC File at Fixed DateTime=0
Write IC File at Sim End=0
Echo Input=False
Echo Parameters=False
Echo Output=False
Write Detailed= 0
HDF Write Warmup=0
HDF Write Time Slices=0
HDF Flush=0
HDF Compression= 1
HDF Chunk Size= 1
HDF Spatial Parts= 1
HDF Use Max Rows=0
HDF Fixed Rows= 1
Calibration Method= 0
Calibration Iterations= 20
Calibration Max Change=0.05
Calibration Tolerance=0.2
Calibration Maximum=1.5
Calibration Minimum=0.5
Calibration Optimization Method= 1
WQ AD Non Conservative
WQ ULTIMATE=-1
WQ Max Comp Step=1HOUR
WQ Output Interval=15MIN
WQ Output Selected Increments= 0
WQ Create Restart=0
WQ Fixed Restart=0
WQ System Summary=0
WQ Write To DSS=0
Sorting and Armoring Iterations= 10
XS Update Threshold= 0.02
Bed Roughness Predictor= 0
Processes Affected by Predictor=Sediment Only
Hydraulics Update Threshold= 0.02
Energy Slope Method= 1
Volume Change Method= 1
Sediment Retention Method= 0
Sediment TS Multiplier= 1
Warm Up Method= 0
XS Weighting Method= 0
Number of US Weighted Cross Sections= 1
Number of DS Weighted Cross Sections= 1
Upstream XS Weight=0
Main XS Weight=1
Downstream XS Weight=0
Number of DS XS's Weighted with US Boundary= 1
Upstream Boundary Weight= 1
Weight of XSs Associated with US Boundary= 0
Number of US XS's Weighted with DS Boundary= 1
Downstream Boundary Weight= 0.5
Weight of XSs Associated with DS Boundary= 0.5
Percentile Method= 0
Sediment Output Level= 3
Mass or Volume Output= 0
Output Increment Type= 1
Profile and TS Output Increment= 1
Transport Output Increment 1
XS Output Flag= 0
XS Output Increment= 10
Read HDF5 Sediment Hotstart= 0
Sediment Hotstart Type= 0
Write Gradation File= 0
Read Gradation Hotstart= 0
Write HDF5 File= 1
Write Binary Output= 1
Write DSS Sediment File= 0
DSS Sediment Output Type= 1
SV Curve= 0
Specific Gage Flag= 0
Subcell Erosion Methods= 0
Subcell Deposition Methods= 0
Advection Scheme= 1
Matrix Solver= 0
Implicit Weighting Factor= 1
Maximum Outer Loop Convergence Iterations= 5
Convergence Maximum Absolute= 0.001
Convergence RMSE= 0.0001
Grain Fractions Max Abs Error= 0.001
Max Subgrid Regions= 1
Max Subgrid Length Scale= 3.402823E+38
Initial Layer Thickness= 3
Min Layer Thickness= 0.1
Max Layer Thickness= 6
Number of Layers= 5

--- GraveCkT2.f01 (steady flow) ---

Flow Title=Flow
Program Version=6.60
Number of Profiles= 1
Profile Names=P100yr
River Rch & RM=GraveCKT2,Main            ,1384
     620
Boundary for River Rch & Prof#=GraveCKT2,Main            , 1
Up Type= 0
Dn Type= 3
Dn Slope=0.04
DSS Import GetInterval= 0
DSS Import GetPeak= 0
DSS Import FillOption= 0

--- GraveCkT2.g01 (geometry) ---

Geom Title=Geometry
Program Version=6.60

River Reach=GraveCKT2       ,Main
Reach XY= 30
1622567.43452314496382.478661314 1622635.6673263496416.838828817
1622664.17908031496421.225302979 1622716.0844883496418.300768137
 1622730.4624123496420.9815370591622769.69625773496442.913579807
1622846.94544706 496457.778379471622892.02770597496461.677321807
1622926.38787347496478.9794525651622941.98397088496500.180197567
1622965.13451514496610.571052894 1622974.1509013496626.898448065
1622972.38286021496655.3898608981622981.07083496496667.846528888
1622989.19122556496723.3113129741622994.49403647496735.008468062
1623023.65867631496767.4480357321623061.40105489496799.575924233
 1623105.6939453496810.9610720571623130.49179597496810.493225232
1623148.27128798496805.3465819811623182.50448722496776.523148805
1623211.01624122496771.4057049751623249.27535105496778.716385901
1623276.56827547496809.4210488951623402.17530772496874.593162641
1623435.23888989496900.9503933941623465.02754422 496936.97755231
1623511.81550838497022.1319095641623579.63394231 497096.36043565

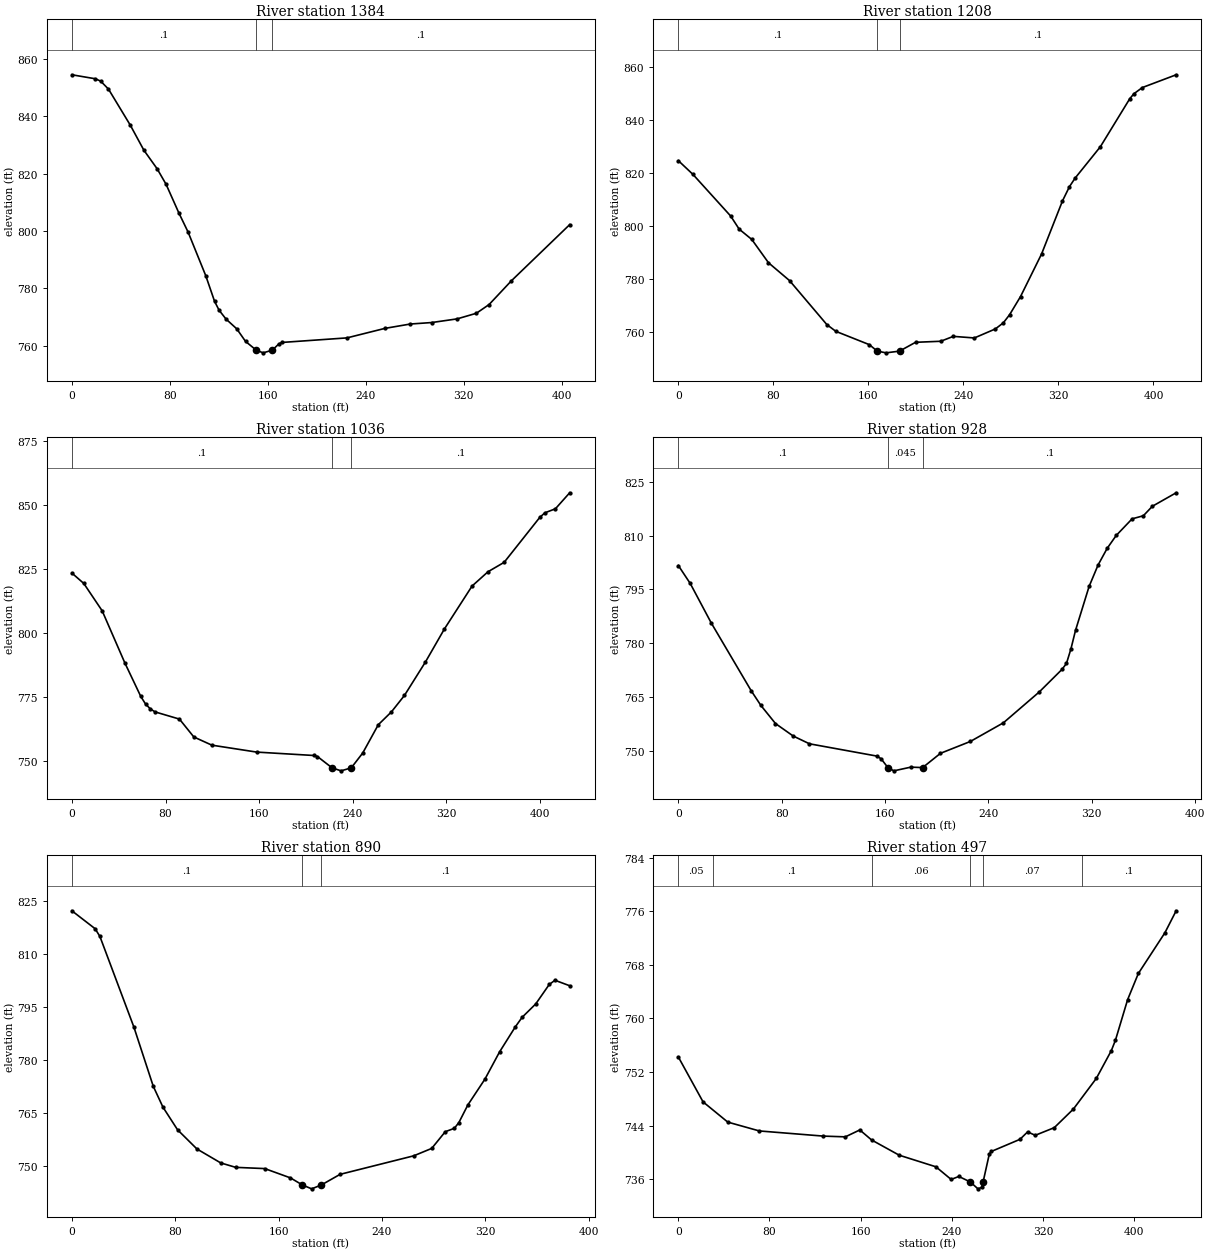
Type RM Length L Ch R = 1 ,1384    ,177,176.4,177.5
XS GIS Cut Line= 3
1622532.44265366496540.0555024131622624.10238684496339.981031049
1622566.93825217496162.575095848
#Sta/Elev= 30
       0  854.56    19.1  853.17    23.5  852.35    29.9  849.55    47.7  836.97
    58.8  828.22    69.6  821.75    76.9  816.34    87.3  806.37    94.9  799.63
   109.3  784.43   116.5  775.47   120.2  772.35   125.9  769.24   134.6  765.86
   141.8  761.46  150.56758.3905   156.2  757.46  163.67758.3918     169  760.57
   171.5  761.09   224.6  762.68   255.6     766   276.3  767.52   293.8  768.04
   314.6  769.32   330.3  771.28   340.7  774.33   358.9  782.62   406.5  802.23
#Mann= 3 ,-1,0
       0      .1       0  150.56    .045       0  163.67      .1       0
Bank Sta=150.56,163.67
XS Rating Curve= 0 ,0
Exp/Cntr(USF)=0,0
Exp/Cntr=0.3,0.1

Type RM Length L Ch R = 1 ,1208    ,165.4,171.5,172.2
XS GIS Cut Line= 2
1622699.43164825496599.7154865391622855.65574397496210.818769971
#Sta/Elev= 30
       0   824.8    12.3  819.61    44.1  803.86    51.2  798.94    61.8  795.06
    75.9  786.24    93.6  779.51     125   762.9   132.6  760.34   160.8  755.31
  167.46752.8643   174.9  752.22   186.2752.8658   199.7   756.2   220.9  756.59
   231.5  758.44   249.2  757.84   266.9  761.25   273.6  763.55   278.9  766.63
   288.1  773.49   305.8  789.56   323.4   809.6   329.3     815     334  818.19
   355.3  830.06     380  848.16   383.5  850.06   390.6   852.4   419.1  857.23
#Mann= 3 ,-1,0
       0      .1       0  167.46    .045       0   186.2      .1       0
Bank Sta=167.46,186.2
XS Rating Curve= 0 ,0
Exp/Cntr(USF)=0,0
Exp/Cntr=0.3,0.1

Type RM Length L Ch R = 1 ,1036    ,101,108.1,115.1
XS GIS Cut Line= 3
1622744.72189179496624.6906341071622898.79894651496507.336607972
1623069.64086211496350.864573125
#Sta/Elev= 30
       0  823.41    10.2  819.33    25.9  808.63    45.3  788.23    58.9  775.14
      63  772.15    67.1  770.27    71.1  769.11    91.9   766.3   104.2  759.31
   119.6  756.11   157.9   753.4   206.8  752.07   209.8  751.67  222.28747.2419
     230  746.07  238.69747.2421   248.5  753.05   261.8  764.11     273  769.12
   284.1  775.53     302  788.58   318.2  801.49   341.9  818.33   355.5  823.91
   369.3  827.59   399.7  845.14   404.1  846.96   413.1  848.53   425.3  854.79
#Mann= 3 ,-1,0
       0      .1       0  222.28    .045       0  238.69      .1       0
Bank Sta=222.28,238.69
XS Rating Curve= 0 ,0
Exp/Cntr(USF)=0,0
Exp/Cntr=0.3,0.1

Type RM Length L Ch R = 1 ,928     ,38.4,37.9,36.6
XS GIS Cut Line= 4
1622807.81582484496656.4465400241622939.85538385496583.224279979
1622998.16631702496580.0836459431623163.14297742496519.070579752
#Sta/Elev= 30
       0  801.65     9.2  796.65    25.5  785.61    56.4  766.71    63.9  762.62
    75.2  757.57    88.9  754.09   101.5  751.92   153.6   748.5   156.9  747.76
   162.2  745.29   166.8  744.38   179.9  745.41   189.1745.2906   202.9  749.27
     226  752.57   251.6  757.78   279.4   766.4   296.9  772.66   300.4  774.33
   303.9  778.45   307.4  783.55   317.9   795.8   324.9  801.82   331.9  806.44
   338.9  810.03   351.2  814.67   359.9  815.53   366.9  818.18   385.3  821.94
#Mann= 3 ,-1,0
       0      .1       0   162.2    .045       0   189.1      .1       0
Bank Sta=162.2,189.1
XS Rating Curve= 0 ,0
Exp/Cntr(USF)=0,0
Exp/Cntr=0.3,0.1

Type RM Length L Ch R = 1 ,890     ,397.7,393.3,379.8
XS GIS Cut Line= 4
1622805.36551306496693.0664947271622937.40507207496619.844234682
1622995.71600524496616.7036006461623160.69266564496555.690534455
#Sta/Elev= 30
       0  822.23      18  817.14    21.7  814.95      48  789.27      63  772.48
    70.5  766.56    81.8  760.15    96.8  754.71   115.2  750.76   126.8   749.5
   149.3  749.15   169.2  746.51   178.4744.5143   185.6  743.41  193.13744.5144
   207.6  747.52   264.6  752.77   278.5  754.87     289  759.61     296  760.56
   299.5  762.18   306.5   767.2   319.7  774.51     331  782.21   343.2  789.32
   348.5  792.04     359  795.82   369.5  801.35   373.9  802.53   385.3  800.98
#Mann= 3 ,-1,0
       0      .1       0   178.4    .045       0  193.13      .1       0
Bank Sta=178.4,193.13
XS Rating Curve= 0 ,0
Exp/Cntr(USF)=0,0
Exp/Cntr=0.3,0.1

Type RM Length L Ch R = 1 ,497     ,187.3,189.5,190.5
XS GIS Cut Line= 3
1623112.07331076497007.4149422871623209.17053754496839.552695013
1623259.73122907496601.828741844
#Sta/Elev= 30
       0  754.23    21.7  747.53    43.4  744.51    71.1  743.19   127.4  742.42
   146.6  742.31   159.3  743.34   169.6  741.85   193.9  739.57   226.1  737.84
   239.5  735.95   246.2   736.4  256.35735.5728     263  734.55   266.3  734.77
  267.52735.5726     273  739.76   274.9  740.14   299.9  741.94   306.6  743.05
   313.3  742.54     330  743.68   346.8  746.46   366.9  751.03   380.1  755.18
   383.7  756.73   394.4  762.79   403.8  766.69   427.1  772.76     437  776.05
#Mann= 6 ,-1,0
       0     .05       0      30      .1       0     170     .06       0
  256.35    .045       0  267.52     .07       0  353.92      .1       0
Bank Sta=256.35,267.52
XS Rating Curve= 0 ,0
Exp/Cntr(USF)=0,0
Exp/Cntr=0.3,0.1

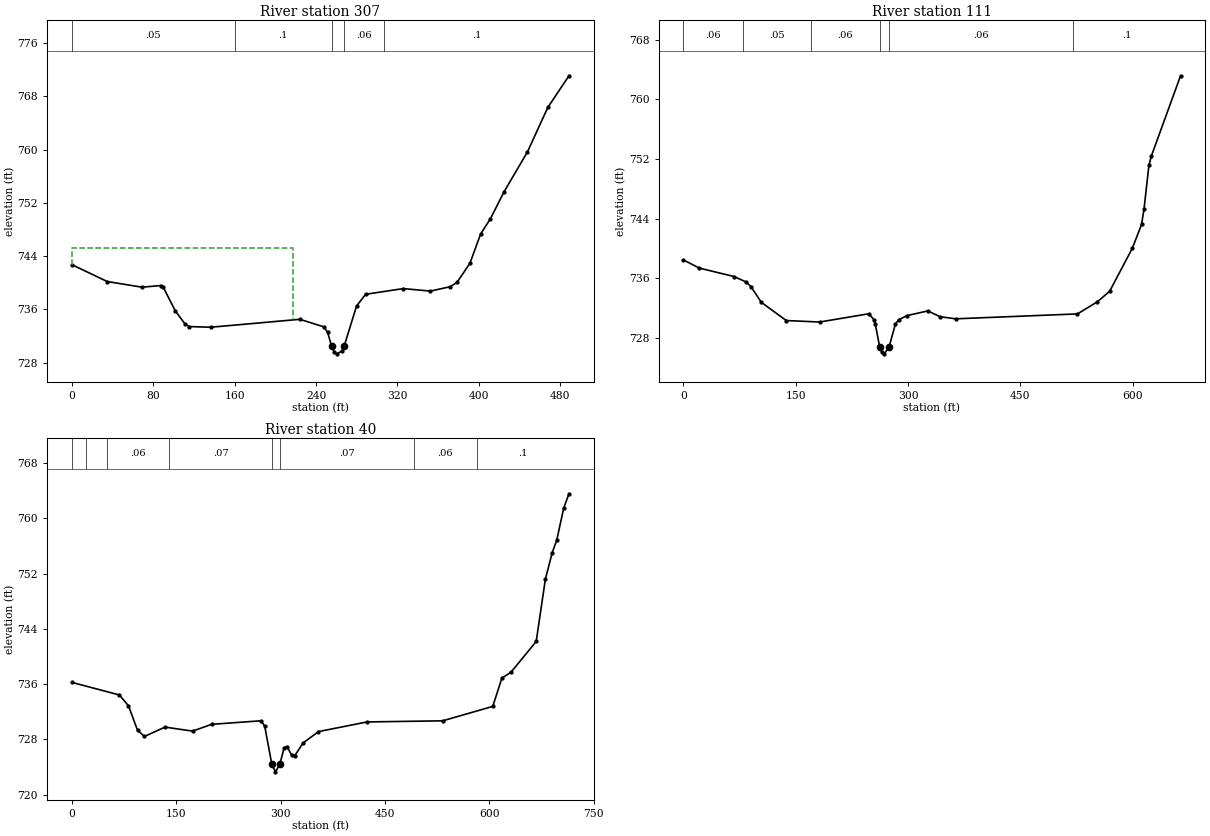
Type RM Length L Ch R = 1 ,307     ,194.4,196.5,198.4
XS GIS Cut Line= 4
1623204.23681738497048.6698142961623349.03771625496930.343381711
1623414.96142238496808.5066563531623432.70279586496646.446324271
#Sta/Elev= 30
       0  742.72    34.8  740.18    68.9  739.33    87.5  739.58    89.9  739.31
   101.5  735.82   111.1  733.82   115.3  733.41   136.5  733.31   224.1   734.5
   247.6  733.37   251.4  732.53  255.32730.4576     258  729.52   260.4  729.31
   265.3  729.72  267.64730.4581   279.8  736.49   288.7  738.26   325.8  739.12
   352.3  738.74   372.1  739.41   378.7  740.08   391.3  742.94   401.8  747.34
   411.3  749.59   424.9   753.7   447.8  759.67   467.8  766.35   488.6  771.11
#Mann= 5 ,-1,0
       0     .05       0     160      .1       0  255.32    .045       0
  267.64     .06       0     307      .1       0
#XS Ineff= 2 , 0
          217.05  745.21
Permanent Ineff=
       F       F
Bank Sta=255.32,267.64
XS Rating Curve= 0 ,0
Exp/Cntr(USF)=0,0
Exp/Cntr=0.3,0.1

Type RM Length L Ch R = 1 ,111     ,71.7,71.2,70
XS GIS Cut Line= 4
1623259.67209376497100.6843757431623456.06046403497059.969713615
  1623595.767638496930.6407868531623587.78437092 496657.61305258
#Sta/Elev= 30
       0  738.47    21.2  737.37    67.5  736.24    83.7  735.51    90.2  734.88
   104.1  732.77   137.4  730.33     182  730.13   247.7  731.24   254.5  730.44
   256.3  729.85  262.24726.7686   265.2  726.04   268.4  725.86  274.68726.7685
   283.1  729.84   287.6  730.44   298.6  730.99   326.5  731.62   342.7  730.85
   363.6  730.56   526.4  731.22   552.9  732.84   569.3  734.25   599.7  740.03
     612  743.23   615.3   745.3   621.8  751.14   625.1  752.41   664.1  763.18
#Mann= 6 ,-1,0
       0     .06       0      80     .05       0     170     .06       0
  262.24    .045       0  274.68     .06       0  520.94      .1       0
Bank Sta=262.24,274.68
XS Rating Curve= 0 ,0
Exp/Cntr(USF)=0,0
Exp/Cntr=0.3,0.1

Type RM Length L Ch R = 1 ,40      ,,,
XS GIS Cut Line= 5
1623291.20599875497148.1848148931623501.36550473497131.084656799
1623567.21149164497048.8490225661623615.12706068496954.814119584
1623633.16579473496662.743040872
#Sta/Elev= 30
       0  736.26    68.2  734.44    81.3  732.89    94.5   729.3   104.4  728.43
     134  729.78   173.5   729.2   200.8  730.18     272   730.7   277.2   729.9
  287.44724.3701   292.6   723.3  298.78724.3693   305.2  726.82   309.1  726.96
   316.2  725.67   320.4  725.65   332.3  727.48   354.4  729.13   424.3  730.53
   532.9  730.69   604.9  732.78     618  736.88   631.2  737.74   667.3  742.19
   680.5  751.21   690.3  755.05   696.9  756.89   706.8   761.5   714.4  763.58
#Mann= 8 ,-1,0
       0     .06       0      20     .05       0      50     .06       0
     140     .07       0  287.44    .045       0  298.78     .07       0
  491.74     .06       0  581.74      .1       0
Bank Sta=287.44,298.78
XS Rating Curve= 0 ,0
Exp/Cntr(USF)=0,0
Exp/Cntr=0.3,0.1
LCMann Table=0

Chan Stop Cuts=-1
Use User Specified Reach Order=0
Composite Channel Slope=5